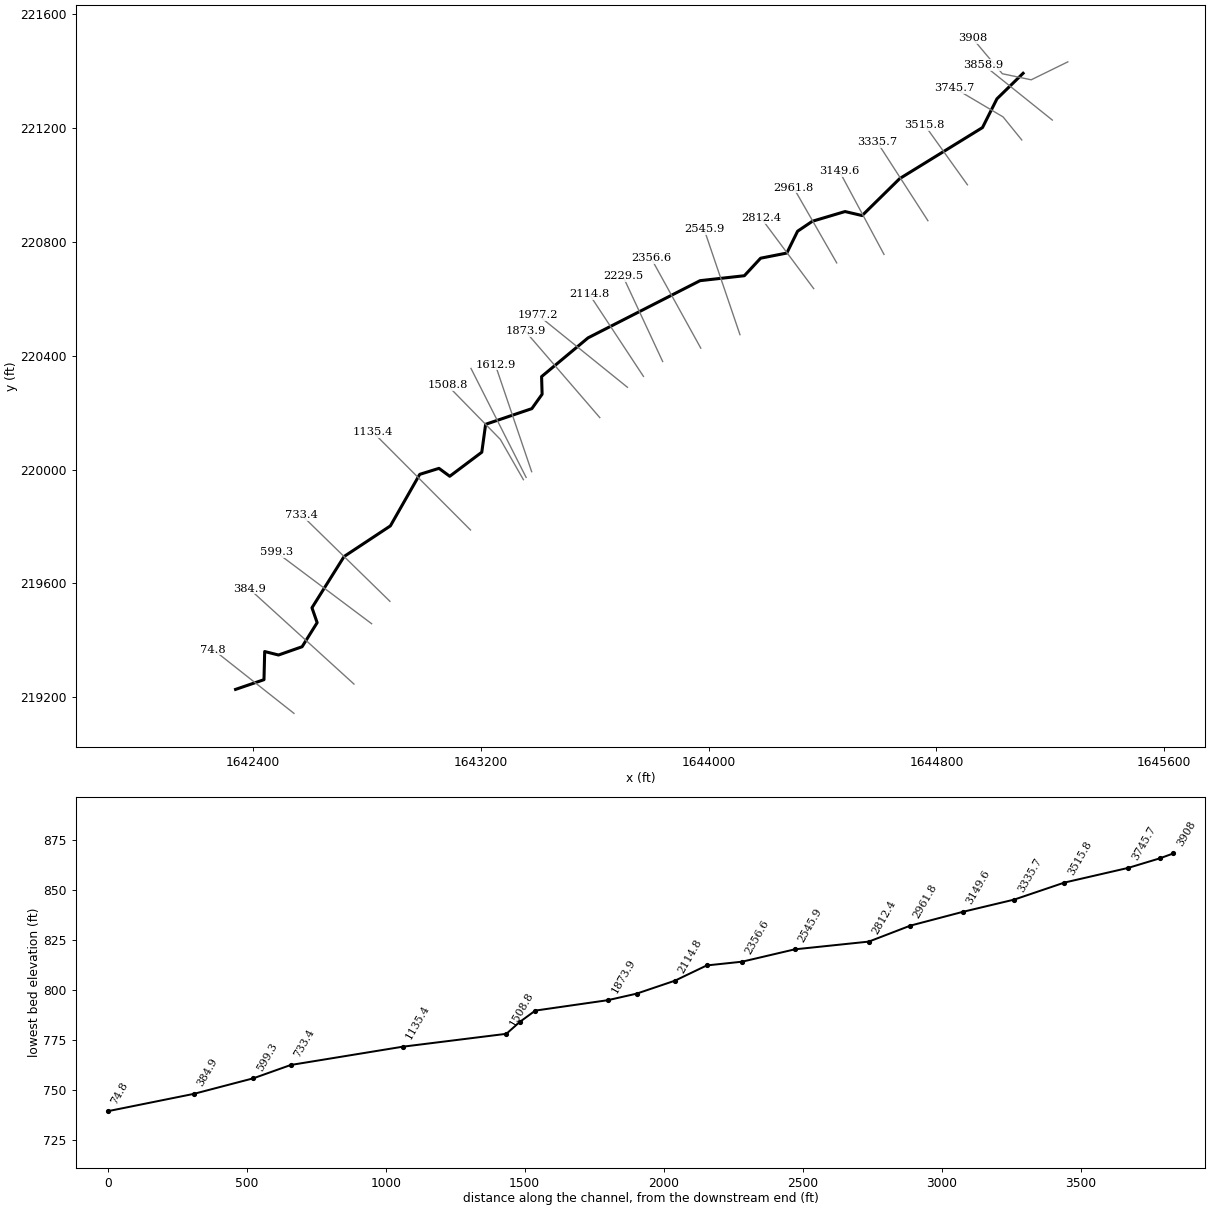
--- mchlnvllbr.prj (project) ---

Proj Title=mchlnvllbr
Current Plan=p01
Default Exp/Contr=0,0
English Units
Geom File=g01
Flow File=f01
Plan File=p01
BEGIN DESCRIPTION:
END DESCRIPTION:
DSS Export Rating Curves= 0
DSS Export Rating Curve Sorted= 0
DSS Export Volume Flow Curves= 0
DXF OffsetX= 0
DXF OffsetY= 0
DXF ScaleX= 0
DXF ScaleY= 0

--- mchlnvllbr.p01 (plan) ---

Plan Title=Approximate Study - 100yr
Program Version=4.00
Geom File=g01
Flow File=f01
Subcritical Flow
K Sum by GR= 0
Std Step Tol= 0.01
Critical Tol= 0.01
Num of Std Step Trials= 20
Max Error Tol= 0.3
Flow Tol Ratio= 0.001
Split Flow NTrial= 30
Split Flow Tol= 0.02
Split Flow Ratio= 0.02
Log Output Level= 0
Friction Slope Method= 1
Unsteady Friction Slope Method= 2
Unsteady Bridges Friction Slope Method= 1
Parabolic Critical Depth
Global Vel Dist= 0 , 0 , 0
Global Log Level= 0
CheckData=True
Encroach Param=-1 ,0,0, 0
Run HTab= 0
Run UNet= 0
Run PostProcess= 0
Run WQNet= 0
UNET Theta= 0
UNET Theta Warmup= 0
UNET ZTol= 0
UNET ZSATol= 0
UNET MxIter= 0
UNET MaxInSteps= 0
UNET DtIC= 0
UNET DtMin= 0
UNET MaxCRTS= 0
UNET WFStab= 0
UNET SFStab= 0
UNET WFX= 1
UNET SFX= 1
UNET DSS MLevel= 1
UNET DZMax Abort= 0
UNET Convert EG Bridges= 0
UNET Use Existing IB Tables= 0
UNET Froude Reduction=False
UNET Froude Limit= 0
UNET Froude Power= 0
UNET Time Slicing=0,0, 5
Write IC File= 0
Echo Input=False
Echo Output=False
Write Detailed= 0
Detailed Automatic Start=False, 0
WQ ULTIMATE=-1
WQ Max Comp Step=1HOUR
WQ Output Interval=15MIN
WQ Output Selected Increments= 0
WQ Output face flow=0
WQ Output face velocity=0
WQ Output face area=0
WQ Output face dispersion=0
WQ Output cell volume=0
WQ Output cell surface area=0
WQ Output cell continuity=0
WQ Output face conc=0
WQ Output face dconc_dx=0
WQ Output face courant=0
WQ Output face peclet=0
WQ Output face adv mass=0
WQ Output face disp mass=0
WQ Output cell mass=0
WQ Output cell source sink temp=0
WQ Output cell source sink nsm=0
WQ Output MaxMinRange=-1
WQ Daily Max Min Mean=-1
WQ Daily Range=0
WQ Daily Time=0
WQ Create Restart=0
WQ Fixed Restart=0
WQ System Summary=False
Sorting and Armoring Iterations= 10
XS Update Threshold= 0.02
Hydraulics Update Threshold= 0.02
Energy Slope Method= 1
Volume Change Method= 0
XS Weighting Method= 0
Number of US Weighted Cross Sections= 1
Number of DS Weighted Cross Sections= 1
Upstream XS Weight=0.25
Main XS Weight=0.5
Downstream XS Weight=0.25
Number of DS XS's Weighted with US Boundary= 1
Upstream Boundary Weight= 1
Weight of XSs Associated with US Boundary= 0
Number of US XS's Weighted with DS Boundary= 1
Downstream Boundary Weight= 0.5
Weight of XSs Associated with DS Boundary= 0.5
Sediment Output Level= 4
Mass or Volume Output= 0
Output Increment Type= 1
Profile and TS Output Increment= 10
XS Output Flag= 0
XS Output Increment= 10
Disregard all LS=0
Disregard all Conn=0
Disregard all Breaches=0
Disregard all Pumps=0

--- mchlnvllbr.f01 (steady flow) ---

Flow Title=USGS Regression Equation
Program Version=4.00
Number of Profiles= 1
Profile Names=P100yr
River Rch & RM=mchlnvllbr,Main            ,3908
     289
River Rch & RM=mchlnvllbr,Main            ,3858.9
     379
River Rch & RM=mchlnvllbr,Main            ,2356.6
     412
River Rch & RM=mchlnvllbr,Main            ,74.8
     447
Boundary for River Rch & Prof#=mchlnvllbr,Main            , 1
Up Type= 0
Dn Type= 3
Dn Slope=0.021021
DSS Import GetInterval= 0
DSS Import GetPeak= 0
DSS Import FillOption= 0

--- mchlnvllbr.g01 (geometry) ---

Geom Title=USGS 3m DEM
Program Version=4.00

River Reach=mchlnvllbr      ,Main
Reach XY= 30
     1645104.534      221391.719     1645012.678       221302.05
      1644961.97      221201.141     1644671.258      221021.935
     1644539.239       220892.09     1644479.176      220906.189
     1644364.576      220872.105     1644312.572      220837.081
     1644274.856      220760.462     1644182.716      220742.319
     1644125.729      220680.801     1643970.142      220663.452
      1643576.67      220462.546     1643413.573      220326.495
     1643415.417      220264.647     1643379.329      220214.045
     1643217.066      220159.044      1643203.59      220061.045
     1643091.094      219976.516     1643053.205      220004.324
      1642985.58      219983.229     1642882.599      219802.254
     1642720.036       219694.77     1642607.202       219514.71
     1642625.407      219462.477     1642572.561      219377.899
     1642489.683      219348.809     1642441.161      219361.058
     1642438.698      219262.193     1642338.903       219228.06

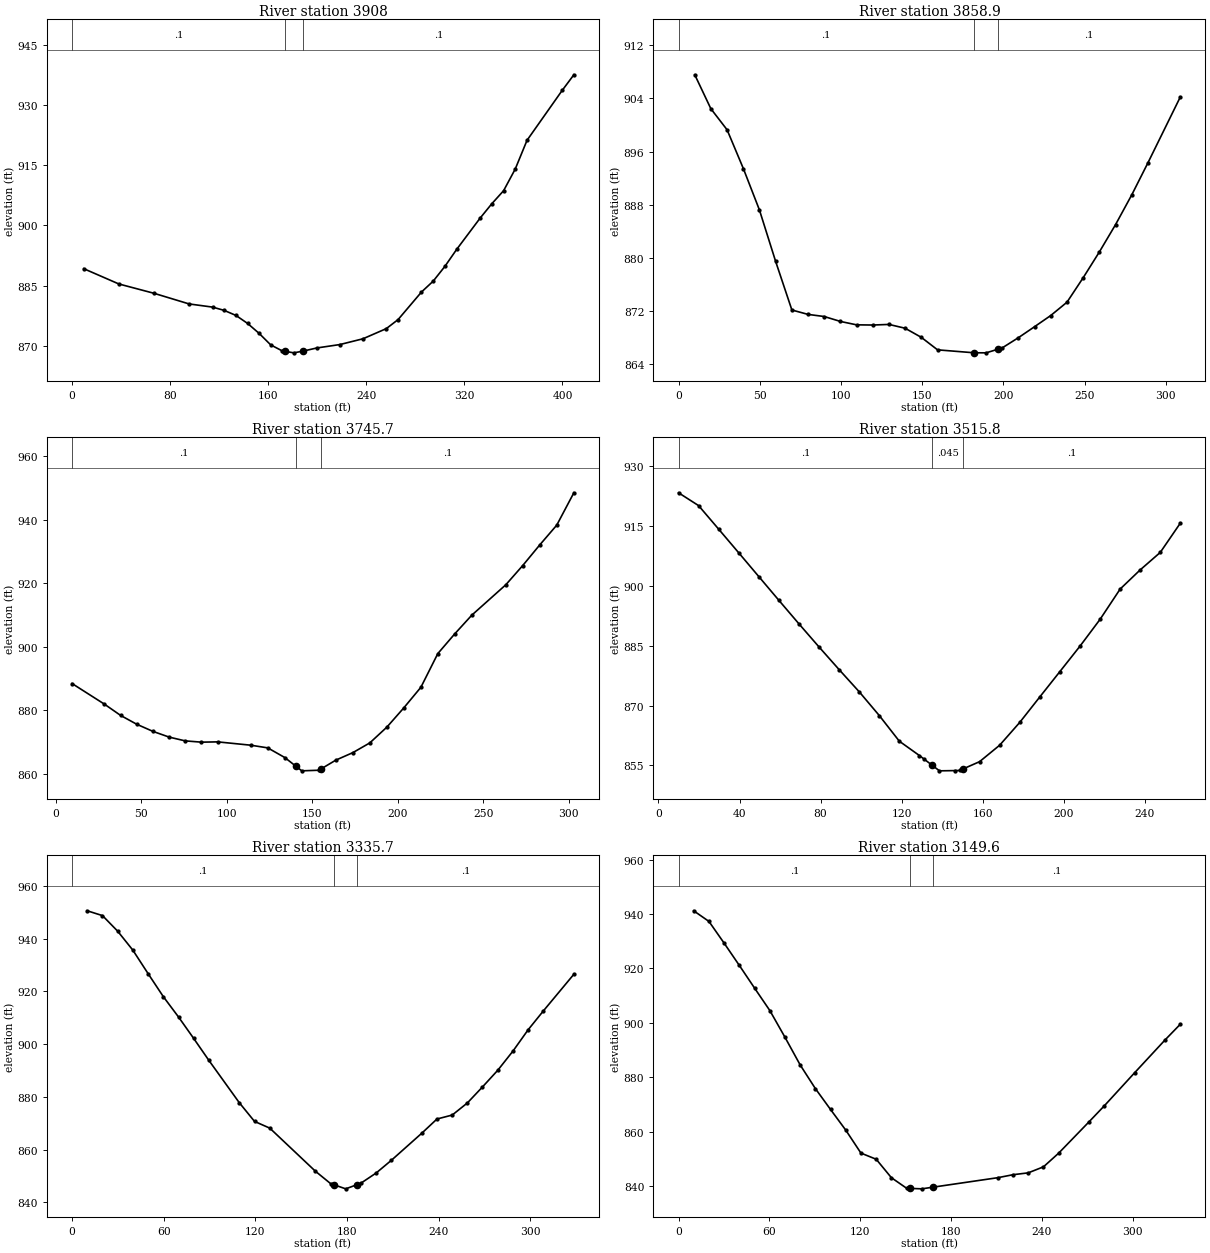
Type RM Length L Ch R = 1 ,3908    ,58.8,49.1,41.3
XS GIS Cut Line= 4
     1645261.621      221431.859     1645133.026       221368.84
     1645031.684       221390.13     1644926.935      221514.466
#Sta/Elev= 30
     9.5  889.22    38.2   885.4    66.8  883.08    95.5  880.42   114.6  879.63
   124.1  878.81   133.7  877.55   143.2  875.55   152.6  873.07     162  870.21
   171.4  868.71   173.4  868.61   180.9  868.22   188.4  868.65   199.7  869.44
   218.5  870.29   237.3  871.73   256.3  874.26   265.9  876.51     285  883.39
   294.6  886.12   304.1  889.79   313.7  894.03   332.8  901.82   342.4  905.43
     352  908.68   361.5  914.09   371.1  921.25   399.8  933.71   409.3   937.6
#Mann= 3 , 0 , 0
       0      .1       0   173.4    .045       0   188.4      .1       0
Bank Sta=173.4,188.4
XS Rating Curve= 0 ,0
Exp/Cntr=0.3,0.1

Type RM Length L Ch R = 1 ,3858.9  ,111.7,113.3,113
XS GIS Cut Line= 2
     1645207.117      221227.471     1644966.109      221420.788
#Sta/Elev= 30
      10  907.55    19.9  902.45    29.9  899.28    39.9  893.46    49.8  887.24
    59.8  879.49    69.8  872.19    79.7  871.53    89.7  871.21    99.7  870.47
   109.6  869.96   119.6  869.93   129.6  870.02   139.5  869.45   149.5  868.08
   159.5   866.2   181.9  865.76   189.4  865.75   196.9  866.31   199.3  866.49
   209.3  868.03   219.3  869.69   229.2  871.36   239.2  873.36   249.2  877.05
   259.1   880.9   269.1  885.02   279.1   889.5     289  894.29     309  904.22
#Mann= 3 , 0 , 0
       0      .1       0   181.9    .045       0   196.9      .1       0
Bank Sta=181.9,196.9
XS Rating Curve= 0 ,0
Exp/Cntr=0.3,0.1

Type RM Length L Ch R = 1 ,3745.7  ,239.3,229.9,220.4
XS GIS Cut Line= 3
     1645099.813      221157.638     1645034.239      221238.542
     1644863.064      221339.884
#Sta/Elev= 30
     9.5  888.43    28.4  881.96    37.9  878.41    47.3  875.64    56.8  873.39
    66.3  871.59    75.7   870.4    85.2     870    94.7  870.09   114.1  869.04
     124   868.2     134  865.15   140.4 862.455   143.9  860.98   153.9  861.17
   155.4  861.65   163.8  864.34   173.8  866.71   183.7  869.76   193.7  874.73
   203.6  880.78   213.6  887.26   223.5  897.85   233.4  904.05   243.4  909.94
   263.3   919.5   273.2  925.55   283.2  932.06   293.1  938.25   303.1  948.42
#Mann= 3 , 0 , 0
     9.5      .1       0   140.4    .045       0   155.4      .1       0
Bank Sta=140.4,155.4
XS Rating Curve= 0 ,0
Exp/Cntr=0.3,0.1

Type RM Length L Ch R = 1 ,3515.8  ,181.2,180.1,179
XS GIS Cut Line= 2
     1644909.051      221000.089     1644759.166      221209.587
#Sta/Elev= 30
     9.9  923.37    19.8  920.15    29.7  914.25    39.6  908.32    49.5  902.36
    59.4  896.41    69.4  890.45    79.3  884.66    89.2  878.99    99.1  873.44
     109  867.48   118.9  861.04   128.8  857.45   131.2  856.52   135.2 854.968
   138.7  853.61   146.2  853.67   148.6   853.7   150.2 854.057   158.5  855.91
   168.4  860.03   178.3  865.74   188.2  872.13   198.1  878.48   208.1  884.91
     218  891.63   227.9  899.22   237.8  904.03   247.7  908.41   257.6  915.75
#Mann= 3 , 0 , 0
     9.9      .1       0   135.2    .045       0   150.2      .1       0
Bank Sta=135.2,150.2
XS Rating Curve= 0 ,0
Exp/Cntr=0.3,0.1

Type RM Length L Ch R = 1 ,3335.7  ,188,186.1,184.3
XS GIS Cut Line= 2
     1644770.237       220874.05     1644592.249      221149.974
#Sta/Elev= 30
     9.9  950.57    19.9  948.74    29.8  942.86    39.8  935.62    49.7  926.78
    59.7  918.02    69.7  910.26    79.6  902.15    89.5  893.86   109.4  877.81
   119.4  870.69   129.4  868.13   159.2  851.82   169.2  847.09   171.6  846.61
   179.1  845.11   186.6  846.72     189  847.24     199  851.11     209  855.95
   228.9  866.22   238.8  871.59   248.8   873.1   258.7  877.68   268.6  883.76
   278.6  890.08   288.6   897.4   298.5  905.46   308.5  912.63   328.4  926.49
#Mann= 3 , 0 , 0
       0      .1       0   171.6    .045       0   186.6      .1       0
Bank Sta=171.6,186.6
XS Rating Curve= 0 ,0
Exp/Cntr=0.3,0.1

Type RM Length L Ch R = 1 ,3149.6  ,186.2,187.8,189.4
XS GIS Cut Line= 2
     1644616.095      220755.675     1644459.397       221047.78
#Sta/Elev= 28
      10  941.22    20.1   937.3    30.1  929.33    40.2  921.09    50.2   912.8
    60.3  904.53    70.3  894.71    80.4  884.47    90.4  875.81   100.4  868.14
   110.5  860.51   120.5  852.08   130.6  849.81   140.6  843.04   150.7  839.14
   153.2  839.09   160.7  838.93   168.2  839.55   210.9  843.03     221  844.13
     231  844.81   241.1  847.03   251.1  852.04   271.2  863.59   281.3  869.48
   301.3  881.63   321.4   893.7   331.5  899.49
#Mann= 3 , 0 , 0
       0      .1       0   153.2    .045       0   168.2      .1       0
Bank Sta=153.2,168.2
XS Rating Curve= 0 ,0
Exp/Cntr=0.3,0.1

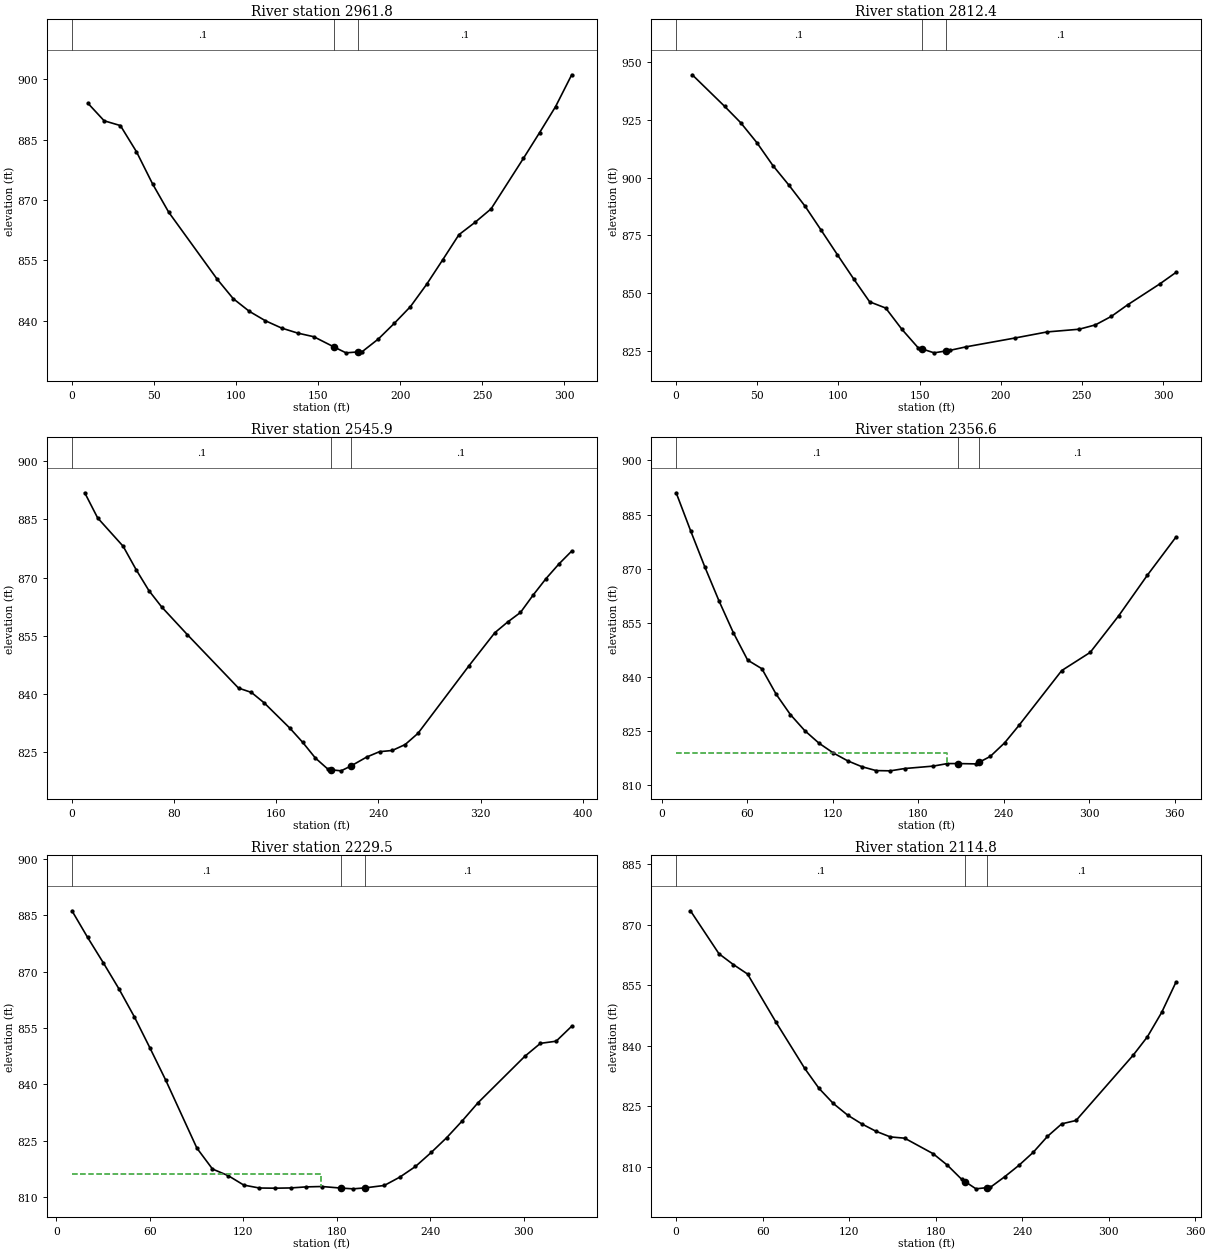
Type RM Length L Ch R = 1 ,2961.8  ,146.5,149.3,152.2
XS GIS Cut Line= 2
     1644450.029      220725.868     1644298.441       220989.87
#Sta/Elev= 29
     9.8  893.98    19.6  889.67    29.5  888.48    39.3  881.98    49.1     874
    58.9  866.99    88.4  850.37    98.2  845.52     108  842.37   117.8  840.03
   127.7  838.21   137.5  836.96   147.3  836.06   159.4  833.56   166.9  832.06
   174.4  832.29   176.8  832.36   186.6  835.49   196.4  839.41   206.2  843.55
     216  849.05   225.9   855.2   235.7  861.39   245.5  864.45   255.3  867.81
     275  880.35   284.8  886.71   294.6  893.21   304.4  901.09
#Mann= 3 , 0 , 0
       0      .1       0   159.4    .045       0   174.4      .1       0
Bank Sta=159.4,174.4
XS Rating Curve= 0 ,0
Exp/Cntr=0.3,0.1

Type RM Length L Ch R = 1 ,2812.4  ,273.8,266.5,259.2
XS GIS Cut Line= 2
     1644369.126      220635.597     1644185.176      220882.566
#Sta/Elev= 27
     9.9  944.58    29.8  930.94    39.7  923.85    49.7  915.18    59.6  905.23
    69.5  896.71    79.5  887.54    89.4  877.14    99.3  866.63   109.3  856.17
   119.2  846.18   129.1  843.48   139.1  834.24     149  826.34   151.4  825.79
   158.9  824.07   166.4  824.91   168.9  825.19   178.8   826.7   208.6  830.48
   228.5  833.13   248.3  834.31   258.3  836.19   268.2  839.91   278.1  844.86
     298  853.96   307.9  858.91
#Mann= 3 , 0 , 0
       0      .1       0   151.4    .045       0   166.4      .1       0
Bank Sta=151.4,166.4
XS Rating Curve= 0 ,0
Exp/Cntr=0.3,0.1

Type RM Length L Ch R = 1 ,2545.9  ,185.8,189.3,192.9
XS GIS Cut Line= 2
     1644110.234       220473.79     1643984.195      220844.243
#Sta/Elev= 30
      10  891.88    20.1   885.4    40.1  878.08    50.2  872.08    60.2  866.68
    70.2  862.46    90.3  855.32   130.4  841.53   140.5  840.41   150.5  837.72
   170.6   831.2   180.6  827.56   190.6  823.49   200.7  820.54   203.2  820.45
   210.7  820.19   218.2   821.4   230.8  823.75   240.8  825.13   250.8  825.44
   260.9  826.97   270.9  829.85     311  847.34   331.1   855.8   341.1  858.55
   351.2  861.03   361.2  865.55   371.2  869.76   381.3  873.53   391.3  876.85
#Mann= 3 , 0 , 0
       0      .1       0   203.2    .045       0   218.2      .1       0
Bank Sta=203.2,218.2
XS Rating Curve= 0 ,0
Exp/Cntr=0.3,0.1

Type RM Length L Ch R = 1 ,2356.6  ,128.6,127.1,125.6
XS GIS Cut Line= 2
     1643972.641      220426.468     1643798.059      220742.418
#Sta/Elev= 30
      10  891.03    20.1  880.55    30.1  870.51    40.1  861.06    50.1  852.32
    60.2  844.68    70.2  842.29    80.2  835.24    90.2   829.6   100.3  825.15
   110.3  821.67   120.3  818.98   130.4  816.79   140.4  815.16   150.4  814.08
   160.4  814.01   170.5  814.65   190.5  815.32   200.5  816.02   207.9 816.027
   220.6  815.93   222.9 816.406   230.6     818   240.7  821.77   250.7  826.57
   280.8  841.79   300.8  846.82   320.9  857.01   340.9  868.18     361  878.75
#Mann= 3 , 0 , 0
      10      .1       0   207.9    .045       0   222.9      .1       0
#XS Ineff= 2 , 0
       0     200     819               0
Permanent Ineff=
       F       F
Bank Sta=207.9,222.9
XS Rating Curve= 0 ,0
Exp/Cntr=0.3,0.1

Type RM Length L Ch R = 1 ,2229.5  ,111.4,114.7,118
XS GIS Cut Line= 2
     1643838.795      220379.523     1643699.122      220679.373
#Sta/Elev= 30
      10  886.18      20  879.12    30.1  872.34    40.1  865.43    50.1   857.9
    60.1  849.62    70.2  841.07    90.2  822.98   100.2  817.42   110.3  815.65
   120.3  813.14   130.3  812.36   140.3  812.31   150.4  812.38   160.4  812.66
   170.4  812.76     183  812.33   190.5  812.14     198  812.39   210.5  813.04
   220.5  815.27   230.5  818.09   240.6  821.82   250.6  825.79   260.6  830.27
   270.6  835.04   300.7  847.43   310.7  850.88   320.8  851.45   330.8  855.44
#Mann= 3 , 0 , 0
      10      .1       0     183    .045       0     198      .1       0
#XS Ineff= 2 , 0
       0     170     816               0
Permanent Ineff=
       F       F
Bank Sta=183,198
XS Rating Curve= 0 ,0
Exp/Cntr=0.3,0.1

Type RM Length L Ch R = 1 ,2114.8  ,130.6,137.6,144.6
XS GIS Cut Line= 2
      1643771.29      220327.312     1643580.528      220616.862
#Sta/Elev= 30
     9.9  873.48    29.7  862.81    39.6  860.15    49.5  857.79    69.3   845.8
    89.2  834.35    99.1  829.41     109  825.67   118.9  822.79   128.8  820.59
   138.7  818.76   148.6  817.37   158.5  817.06   178.3   813.2   188.2  810.34
   198.1  806.84   200.5  806.27     208  804.49   215.5  804.79     218  804.88
   227.9  807.49   237.8  810.33   247.7  813.55   257.6  817.51   267.5  820.62
   277.4  821.45     317  837.63   326.9  842.21   336.8  848.25   346.7  855.75
#Mann= 3 , 0 , 0
       0      .1       0   200.5    .045       0   215.5      .1       0
Bank Sta=200.5,215.5
XS Rating Curve= 0 ,0
Exp/Cntr=0.3,0.1

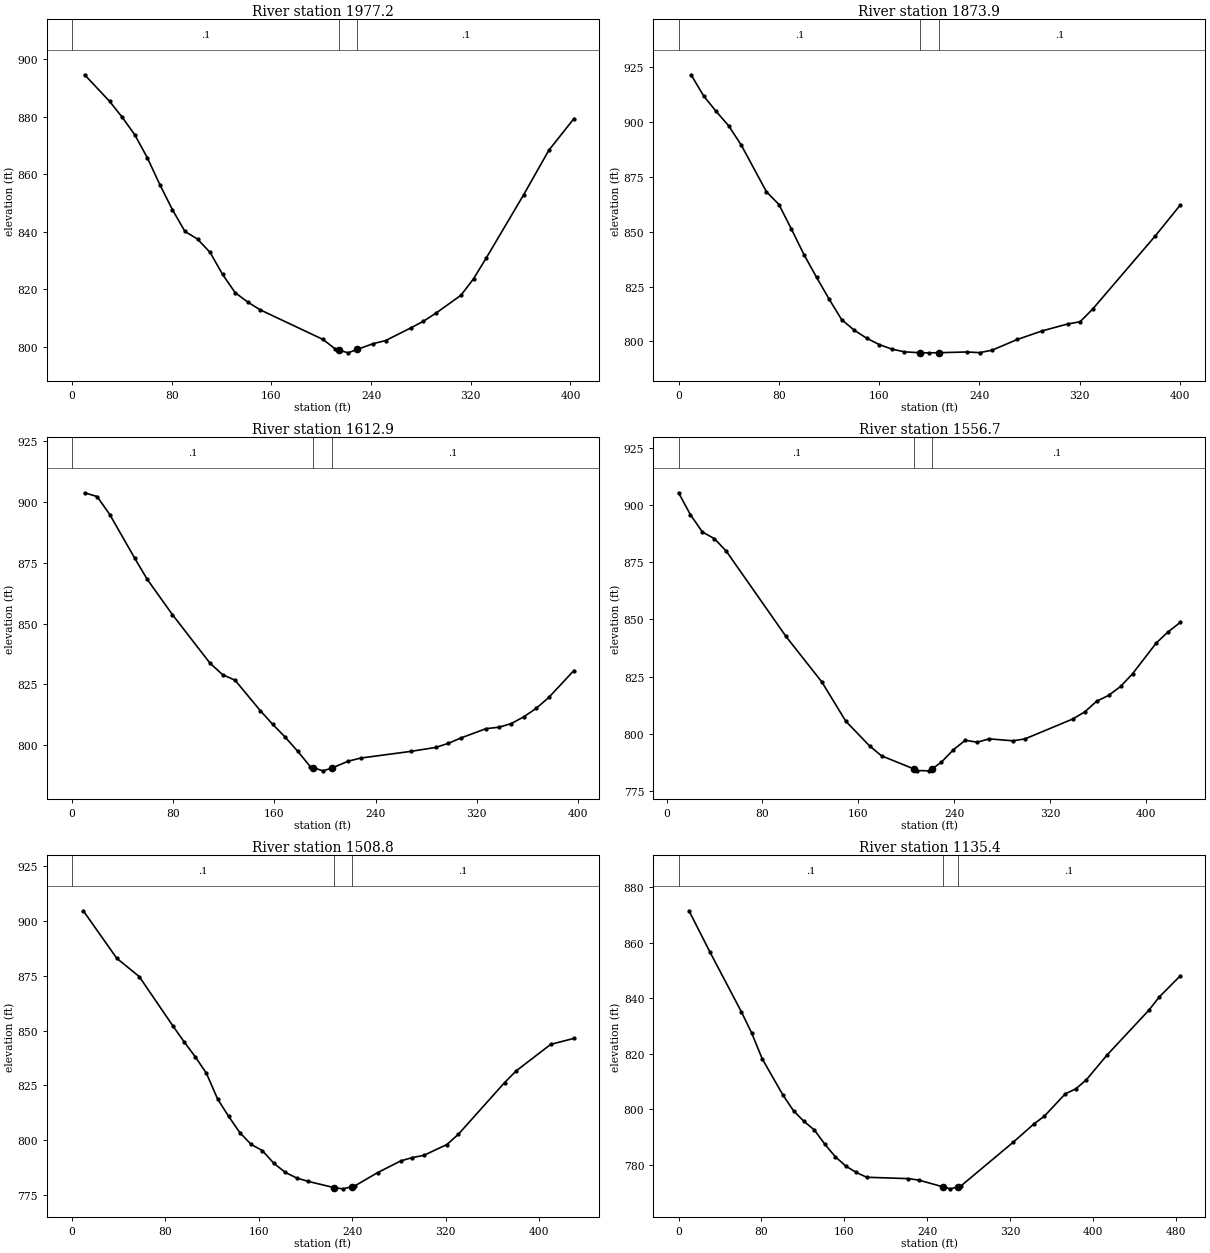
Type RM Length L Ch R = 1 ,1977.2  ,107.4,103.3,99.2
XS GIS Cut Line= 2
     1643715.084      220288.989     1643401.688      220541.919
#Sta/Elev= 30
    10.1  894.52    30.2  885.26    40.3  879.75    50.3  873.72    60.4   865.7
    70.5  856.35    80.5  847.71    90.6  840.13   100.7  837.49   110.8  832.85
   120.8  825.21   130.9  818.89     141  815.63     151  812.93   201.4  802.65
   211.4   799.3     214  798.97   221.5  798.01     229  799.23   241.6  801.19
   251.7  802.28   271.8  806.66   281.9  808.96     292  811.78   312.1  817.99
   322.2  823.72   332.3  830.86   362.5  852.95   382.6  868.31   402.7  879.28
#Mann= 3 , 0 , 0
       0      .1       0     214    .045       0     229      .1       0
Bank Sta=214,229
XS Rating Curve= 0 ,0
Exp/Cntr=0.3,0.1

Type RM Length L Ch R = 1 ,1873.9  ,269.3,261,252.5
XS GIS Cut Line= 2
     1643617.999      220182.537     1643356.553      220485.713
#Sta/Elev= 30
      10  921.63      20     912      30  904.93      40  898.35      50  889.59
    70.1  868.28    80.1  862.42    90.1  851.16   100.1  839.54   110.1  829.23
   120.1  819.28   130.1  809.93   140.1  805.09   150.1  801.43   160.1  798.53
   170.1  796.46   180.2  795.21   192.7  794.79   200.2  794.75   207.7  794.81
   230.2  795.14   240.2  794.84   250.2  795.97   270.2  800.84   290.2  804.78
   310.3   807.9   320.3  808.93   330.3  814.67   380.3  848.09   400.3  862.22
#Mann= 3 , 0 , 0
       0      .1       0   192.7    .045       0   207.7      .1       0
Bank Sta=192.7,207.7
XS Rating Curve= 0 ,0
Exp/Cntr=0.3,0.1

Type RM Length L Ch R = 1 ,1612.9  ,53.2,56.2,62.1
XS GIS Cut Line= 2
     1643378.695      219992.626     1643250.952      220368.189
#Sta/Elev= 30
     9.9  903.69    19.8  902.14    29.8  894.76    49.6  876.76    59.5  868.09
    79.3   853.7   109.1   833.7     119  829.03   128.9  826.72   148.8  814.24
   158.7  808.57   168.6   803.3   178.5   797.5   188.4  791.23   190.8  790.82
   198.3  789.53   205.8  790.73   218.2  793.48   228.1  794.77   267.8  797.52
   287.6  799.15   297.5  800.84   307.4  803.03   327.3  806.85   337.2  807.42
   347.1  808.89     357  811.67   366.9  815.18   376.9  819.67   396.7  830.69
#Mann= 3 , 0 , 0
       0      .1       0   190.8    .045       0   205.8      .1       0
Bank Sta=190.8,205.8
XS Rating Curve= 0 ,0
Exp/Cntr=0.3,0.1

Type RM Length L Ch R = 1 ,1556.7  ,42.8,47.9,51.6
XS GIS Cut Line= 2
     1643359.243       219972.53     1643165.715      220355.146
#Sta/Elev= 30
      10  905.31    19.9  895.76    29.9  888.17    39.9  885.29    49.9  879.76
    99.7  842.52   129.6  822.66   149.6   805.5   169.5  794.69   179.5  790.35
   206.9 784.565   209.4  783.94   219.4  783.82   221.9 784.767   229.3  787.57
   239.3  792.99   249.3  797.17   259.3  796.33   269.2  797.79   289.2  796.94
   299.1  797.77     339  806.46     349  809.56     359  814.26   368.9  816.76
   378.9  820.67   388.9  826.21   408.8  839.73   418.8  844.61   428.8   848.7
#Mann= 3 , 0 , 0
      10      .1       0   206.9    .045       0   221.9      .1       0
Bank Sta=206.9,221.9
XS Rating Curve= 0 ,0
Exp/Cntr=0.3,0.1

Type RM Length L Ch R = 1 ,1508.8  ,370.3,373.4,374.3
XS GIS Cut Line= 3
      1643349.74      219964.523     1643268.836      220105.891
     1643082.332      220296.653
#Sta/Elev= 30
     9.6   904.6    38.3  882.94    57.5  874.64    86.2  852.25    95.8     845
   105.4  838.13     115  830.62   124.6  818.87   134.1  810.91   143.7  803.49
   153.3  798.18   162.9  795.35   172.8  789.55   182.6  785.39   192.5  782.82
   202.4  781.28   224.5  778.45     232  777.91   239.5  778.87   241.9  779.18
   261.7  785.32   281.5  790.64   291.3  792.15   301.2  793.16     321  798.11
   330.9  802.83   370.4  826.33   380.3  831.65   409.9  843.74   429.7  846.46
#Mann= 3 , 0 , 0
       0      .1       0   224.5    .045       0   239.5      .1       0
Bank Sta=224.5,239.5
XS Rating Curve= 0 ,0
Exp/Cntr=0.3,0.1

Type RM Length L Ch R = 1 ,1135.4  ,401.3,401.9,402
XS GIS Cut Line= 2
      1643163.94       219787.88      1642822.16      220130.548
#Sta/Elev= 30
    10.1  871.48    30.2   856.7    60.5  835.22    70.6  827.45    80.7  818.22
   100.8  805.13   110.9  799.53     121  795.71   131.1  792.58   141.2  787.45
   151.2     783   161.3  779.66   171.4  777.34   181.5  775.61   221.8  775.11
   231.9  774.58   254.7  772.18   262.2  771.44   269.7  772.17   272.2  772.42
   322.7  788.18   342.8  794.79   352.9   797.6   373.1  805.65   383.1  807.39
   393.2  810.61   413.4  819.62   453.7  835.73   463.8  840.52     484   848.1
#Mann= 3 , 0 , 0
       0      .1       0   254.7    .045       0   269.7      .1       0
Bank Sta=254.7,269.7
XS Rating Curve= 0 ,0
Exp/Cntr=0.3,0.1

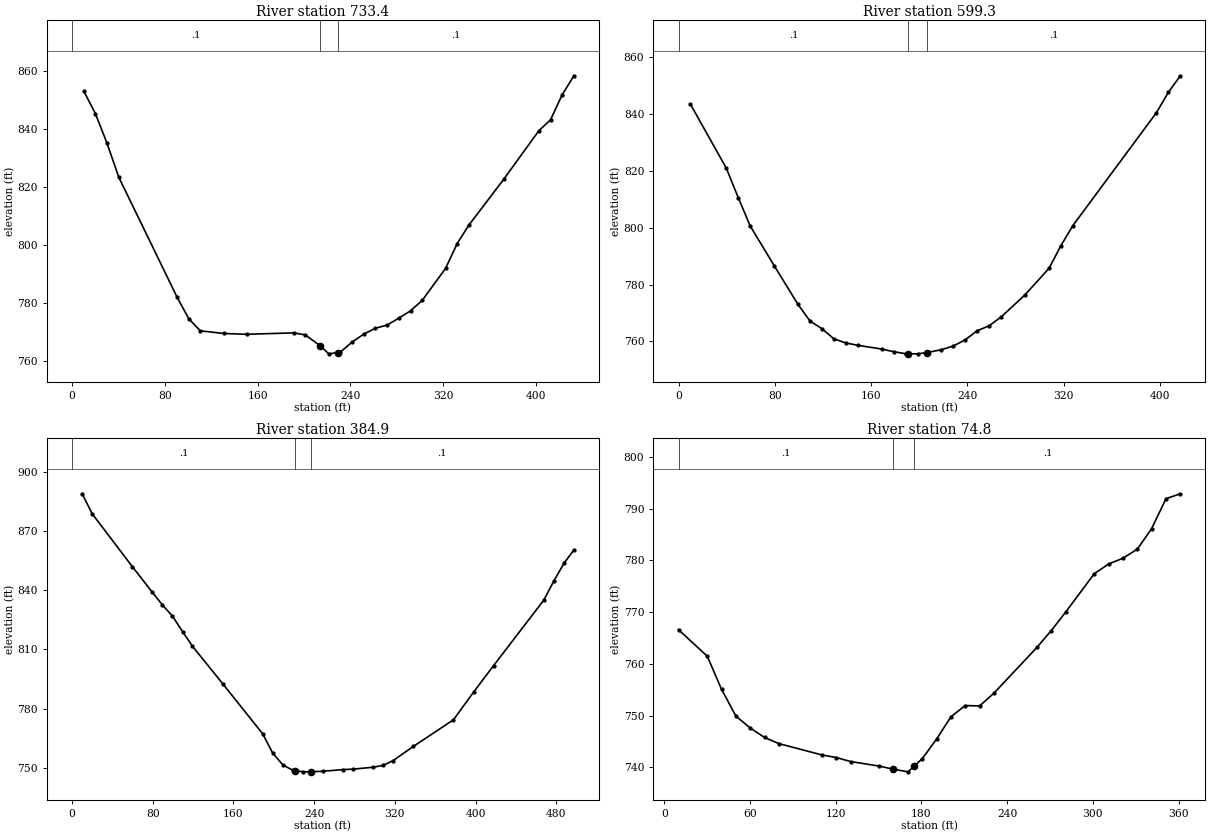
Type RM Length L Ch R = 1 ,733.4   ,131.2,134.2,137.1
XS GIS Cut Line= 2
     1642880.946      219537.408     1642571.293      219839.915
#Sta/Elev= 30
    10.1  852.95    20.1  845.22    30.2  834.91    40.3  823.23    90.6  781.86
   100.7   774.4   110.7  770.25   130.9  769.33     151  769.06   191.3  769.55
   201.3  768.83     214  765.09   221.5  762.31     229  762.76   231.5  762.91
   241.6  766.37   251.7  769.13   261.7  771.14   271.8  772.23   281.9  774.63
     292  777.16     302  780.72   322.2  791.77   332.2  800.34   342.3  806.69
   372.5   822.6   402.7  839.28   412.8  843.06   422.8  851.66   432.9  858.24
#Mann= 3 , 0 , 0
       0      .1       0     214    .045       0     229      .1       0
Bank Sta=214,229
XS Rating Curve= 0 ,0
Exp/Cntr=0.3,0.1

Type RM Length L Ch R = 1 ,599.3   ,214.8,214.4,212.7
XS GIS Cut Line= 2
     1642816.633      219458.804     1642483.161      219708.908
#Sta/Elev= 30
     9.9  843.31    39.7  820.85    49.6  810.51    59.5  800.58    79.4  786.65
    99.2  773.04   109.2  767.17   119.1  764.49     129  760.94   138.9  759.49
   148.9  758.65   168.7  757.35   178.6  756.42   188.6  755.71     191  755.69
   198.5  755.66     206  756.09   218.3   757.1   228.3  758.41   238.2   760.6
   248.1  763.78     258  765.51     268  768.62   287.8  776.39   307.7  785.67
   317.6  793.64   327.5  800.67     397  840.37   406.9  847.51   416.8   853.3
#Mann= 3 , 0 , 0
       0      .1       0     191    .045       0     206      .1       0
Bank Sta=191,206
XS Rating Curve= 0 ,0
Exp/Cntr=0.3,0.1

Type RM Length L Ch R = 1 ,384.9   ,294.2,310.1,315
XS GIS Cut Line= 2
     1642754.702      219246.811     1642386.675      219581.638
#Sta/Elev= 30
      10  889.08    19.9  878.96    59.7  852.11    79.6  839.05    89.6  832.61
    99.5  826.97   109.5  819.11   119.4  811.63   149.3  792.64   189.1  767.09
     199  757.28     209  751.35   218.9  748.62   221.4  748.42   228.9  747.85
   236.4  747.89   248.8  748.15   268.7     749   278.6  749.21   298.5   750.2
   308.5  751.14   318.4  753.59   338.3  760.74   378.1  774.27     398  788.27
   417.9   801.8   467.7  835.07   477.6  844.72   487.6  853.69   497.5  860.55
#Mann= 3 , 0 , 0
       0      .1       0   221.4    .045       0   236.4      .1       0
Bank Sta=221.4,236.4
XS Rating Curve= 0 ,0
Exp/Cntr=0.3,0.1

Type RM Length L Ch R = 1 ,74.8    ,89.6,74.8,58.6
XS GIS Cut Line= 2
     1642544.006       219143.86     1642260.555      219367.763
#Sta/Elev= 30
      10  766.62    30.1  761.49    40.1   755.1    50.2   749.9    60.2  747.62
    70.2  745.79    80.3   744.6   110.4  742.41   120.4  741.92   130.4  741.14
   150.5  740.26   160.1 739.674   170.6  739.15   175.1 740.302   180.6   741.7
   190.6  745.48   200.7  749.81   210.7  751.97   220.7  751.88   230.8  754.37
   260.9  763.21   270.9  766.46   280.9  770.01     301  777.45     311  779.32
   321.1  780.44   331.1  782.19   341.1  786.14   351.2  791.95   361.2  792.89
#Mann= 3 , 0 , 0
      10      .1       0   160.1    .045       0   175.1      .1       0
Bank Sta=160.1,175.1
XS Rating Curve= 0 ,0
Exp/Cntr=0.3,0.1

Chan Stop Cuts=-1
Use User Specified Reach Order=0